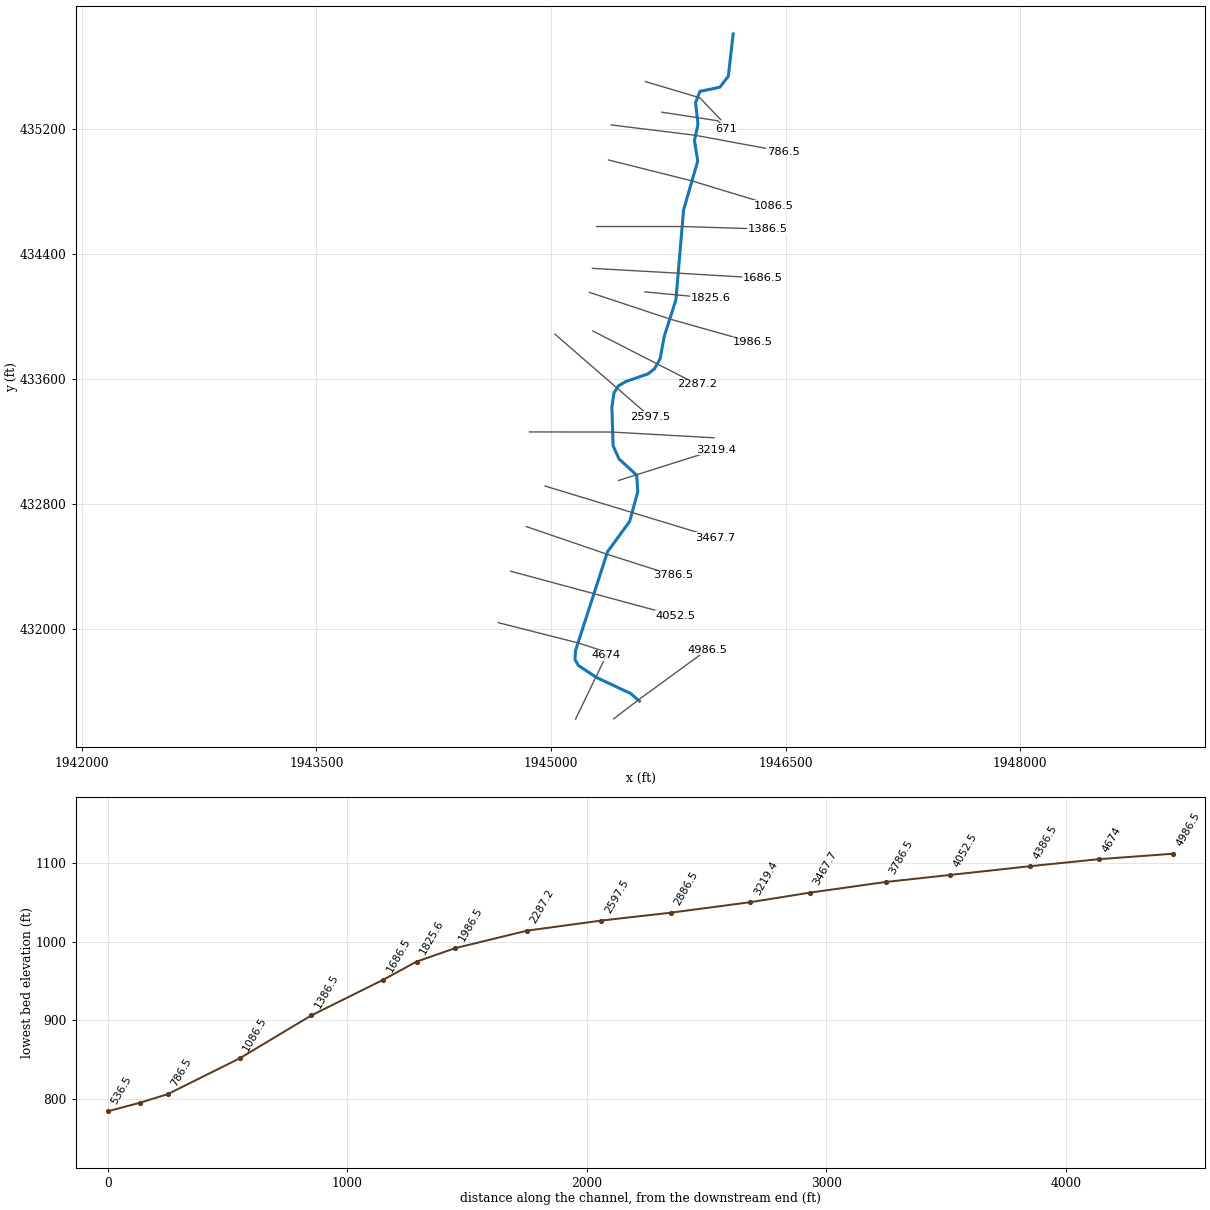
--- SugarCreek.prj (project) ---

Proj Title=SugarCreek
Current Plan=p01
Default Exp/Contr=0,0
English Units
Geom File=g01
Flow File=f01
Plan File=p01
BEGIN DESCRIPTION:
END DESCRIPTION:
DSS Export Rating Curves= 0
DSS Export Rating Curve Sorted= 0
DSS Export Volume Flow Curves= 0
DXF OffsetX= 0
DXF OffsetY= 0
DXF ScaleX= 0
DXF ScaleY= 0

--- SugarCreek.p01 (plan) ---

Plan Title=Floodplain
Program Version=4.00
Geom File=g01
Flow File=f01
K Sum by GR=0
Std Step Tol=0.01
Critical Tol=0.01
Num of Std Step Trials=20
Max Error Tol=0.3
Flow Tol Ratio=0.001
Split Flow NTrial=30
Split Flow Tol=0.02
Split Flow Ratio=0.02
Log Output Level=0
Friction Slope Method=1
Unsteady Friction Slope Method=2
Unsteady Bridges Friction Slope Method=1
Global Log Level=0
CheckData=False
Run HTab=0
Run UNet=0
Run PostProcess=0
UNET Theta=0
UNET Theta Warmup=0
UNET ZTol=0
UNET ZSATol=0
UNET MxIter=0
UNET MaxInSteps=0
UNET DtIC=0
UNET DtMin=0
UNET MaxCRTS=0
UNET WFStab=0
UNET SFStab=0
UNET WFX=0
UNET SFX=0
UNET DSS MLevel=0
UNET DZMax Abort=0
UNET Convert EG Bridges=0
UNET Use Existing IB Tables=0
UNET Froude Limit=0
UNET Froude Power=0
Write IC File=0
Echo Input=False
Echo Output=False
Write Detailed=0

--- SugarCreek.f01 (steady flow) ---

Flow Title=NFF Regression Equation
Program Version=4.00
Number of Profiles=1
Profile Names=P100yr
River Rch & RM=SugarCreek,Main      ,4986.5
460.6318
River Rch & RM=SugarCreek,Main      ,4674
528.8227
River Rch & RM=SugarCreek,Main      ,2886.5
587.5549
Boundary for River Rch & Prof#=SugarCreek,Main      ,1
Up Type=0
Dn Type=3
Dn Slope=0.107844

--- SugarCreek.g01 (geometry) ---

Geom Title=USGS 3m DEM
Program Version=4.00

River Reach=SugarCreek     ,Main
Reach XY= 30
     1945564.816      431541.153     1945509.056      431589.943
     1945289.502      431692.750     1945174.497      431769.420
     1945152.962      431806.551     1945156.128      431863.959
     1945360.944      432496.040     1945502.086      432689.457
     1945554.361      432879.389     1945547.429      432985.961
     1945434.129      433090.230     1945396.623      433174.350
     1945388.824      433421.304     1945402.353      433512.624
     1945430.644      433557.219     1945479.434      433585.098
     1945620.576      433633.888     1945660.653      433665.253
     1945697.245      433729.725     1945723.383      433872.610
     1945798.310      434107.847     1945847.100      434681.127
     1945937.709      434994.776     1945916.800      435125.463
     1945939.452      435230.013     1945923.769      435367.670
     1945951.450      435439.811     1946078.843      435466.169
     1946133.417      435536.686     1946164.259      435806.877

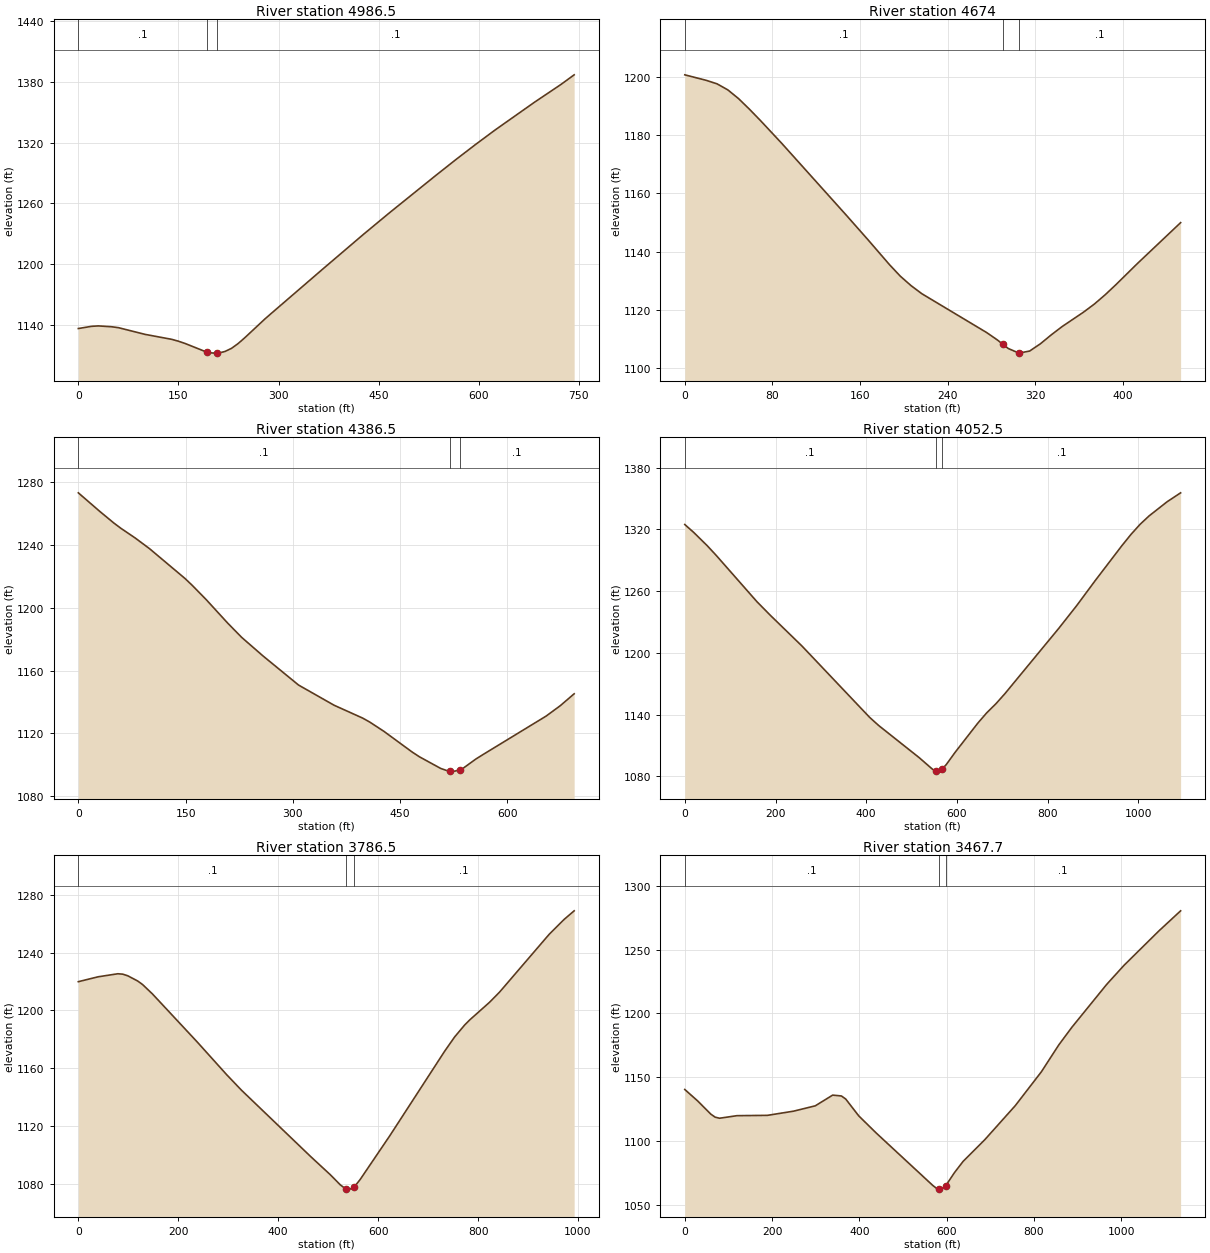
Type RM Length L Ch R = 1 ,4986.5,301.9,312.5,323.6
XS GIS Cut Line= 3
     1945400.285      431427.899     1945559.124      431549.375
     1945997.896      431869.304
#Sta/Elev= 30
       0 1136.35    20.0 1138.55    30.0 1138.94    50.0 1138.10    60.0 1137.22
   100.0 1130.58   140.0 1125.67   150.0 1123.83   160.0 1121.58   190.0 1113.69
   192.5 1113.32   200.0 1112.21   207.5 1112.09   209.8 1112.05   219.7 1113.67
   229.6 1116.80   239.5 1121.54   249.3 1127.16   279.0 1145.44   288.8 1151.10
   367.8 1195.97   427.0 1229.26   466.5 1250.85   535.6 1287.57   565.3 1303.06
   594.9 1318.03   624.5 1332.52   683.8 1360.07   723.2 1377.51   743.0 1387.04
#Mann= 3 , 0 , 0
       0     0.1       0   192.5   0.045       0   207.5     0.1       0
Bank Sta=   192.5,   207.5
Exp/Cntr=0.3,0.1

Type RM Length L Ch R = 1 ,4674,318.4,287.3,254.8
XS GIS Cut Line= 2
     1945156.679      431426.338     1945353.438      431833.909
#Sta/Elev= 30
       0 1200.81    19.7 1198.90    29.5 1197.70    39.4 1195.60    49.2 1192.58
    59.0 1188.98    68.9 1185.14    88.6 1177.19   147.6 1152.43   167.3 1144.02
   186.9 1135.46   196.8 1131.49   206.6 1128.25   216.4 1125.48   275.5 1112.13
   285.3 1109.58   290.4 1108.07   295.2 1106.65   305.0 1105.04   305.4 1105.07
   314.8 1105.76   324.7 1108.28   334.5 1111.32   344.4 1114.17   364.0 1119.15
   373.9 1121.94   383.7 1125.11   393.6 1128.62   413.2 1135.89   452.6 1149.94
#Mann= 3 , 0 , 0
       0     0.1       0   290.4   0.045       0   305.4     0.1       0
Bank Sta=   290.4,   305.4
Exp/Cntr=0.3,0.1

Type RM Length L Ch R = 1 ,4386.5,334.3,334,335.1
XS GIS Cut Line= 3
     1944662.433      432042.978     1945172.819      431913.127
     1945331.576      431862.017
#Sta/Elev= 30
       0 1272.87    29.8 1261.15    49.7 1253.68    59.6 1250.31    79.5 1244.19
    99.4 1237.46   149.0 1218.53   159.0 1214.23   178.9 1205.00   208.7 1190.20
   228.5 1181.02   258.4 1169.21   308.0 1150.76   357.7 1137.94   397.5 1129.80
   407.4 1127.29   427.3 1121.38   467.0 1108.17   477.0 1105.20   506.8 1097.79
   516.7 1096.24   519.1 1096.20   526.6 1096.09   534.1 1097.06   536.5 1097.37
   556.1 1103.82   565.9 1106.60   654.2 1131.05   673.8 1137.58   693.4 1145.21
#Mann= 3 , 0 , 0
       0     0.1       0   519.1   0.045       0   534.1     0.1       0
Bank Sta=   519.1,   534.1
Exp/Cntr=0.3,0.1

Type RM Length L Ch R = 1 ,4052.5,267.5,266,265
XS GIS Cut Line= 2
     1944741.594      432371.744     1945796.925      432086.884
#Sta/Elev= 30
       0 1324.70    19.9 1316.93    49.7 1304.01    69.6 1294.53   159.0 1249.70
   188.8 1236.35   258.4 1206.54   407.4 1137.27   427.3 1129.35   516.7 1098.07
   546.6 1086.60     553 1085.53   556.5 1084.95   566.4 1086.49     568 1087.26
   576.4 1091.29   596.2 1103.37   645.9 1131.57   665.8 1141.71   685.7 1150.36
   705.6 1160.19   824.8 1223.94   864.5 1246.17   904.3 1269.89   963.9 1304.30
   983.8 1315.15  1003.7 1324.88  1023.5 1333.04  1063.3 1346.83  1093.1 1355.52
#Mann= 3 , 0 , 0
       0     0.1       0     553   0.045       0     568     0.1       0
Bank Sta=     553,     568
Exp/Cntr=0.3,0.1

Type RM Length L Ch R = 1 ,3786.5,317.8,318.6,319
XS GIS Cut Line= 3
     1944841.226      432657.436     1945355.792      432481.012
     1945782.871      432344.544
#Sta/Elev= 30
       0 1219.86    39.6 1223.24    79.1 1225.35    89.0 1225.06    98.9 1223.95
   118.7 1220.35   128.6 1217.87   148.4 1211.34   237.4 1178.28   296.7 1155.48
   326.4 1144.70   464.8 1098.74   504.4 1086.05   524.2 1079.11   534.1 1076.52
   536.5 1076.42   544.0 1076.11   551.5 1077.83   553.9 1078.38   563.9 1082.71
   623.7 1113.28   733.3 1171.77   753.2 1181.61   773.1 1189.81   783.1 1193.30
   822.9 1205.56   842.9 1212.59   942.5 1252.76   972.4 1263.06   992.3 1268.96
#Mann= 3 , 0 , 0
       0     0.1       0   536.5   0.045       0   551.5     0.1       0
Bank Sta=   536.5,   551.5
Exp/Cntr=0.3,0.1

Type RM Length L Ch R = 1 ,3467.7,235,248.2,261.8
XS GIS Cut Line= 2
     1944961.150      432916.488     1946048.488      432585.987
#Sta/Elev= 30
       0 1140.43    29.9 1131.36    59.8 1121.09    69.8 1118.74    79.8 1117.94
   119.6 1119.94   189.4 1120.19   249.2 1123.46   299.1 1127.65   338.9 1136.03
   358.9 1135.37   368.8 1132.99   398.8 1119.76   438.6 1106.42   568.2 1065.40
   578.2 1062.72   582.7 1062.59   588.2 1062.44   597.7 1064.90   618.1 1075.35
   638.0 1084.18   687.9 1101.23   757.6 1127.83   817.4 1154.33   857.3 1175.36
   887.2 1189.12   967.0 1222.69  1006.9 1237.68  1086.6 1264.53  1136.5 1280.30
#Mann= 3 , 0 , 0
       0     0.1       0   582.7   0.045       0   597.7     0.1       0
Bank Sta=   582.7,   597.7
Exp/Cntr=0.3,0.1

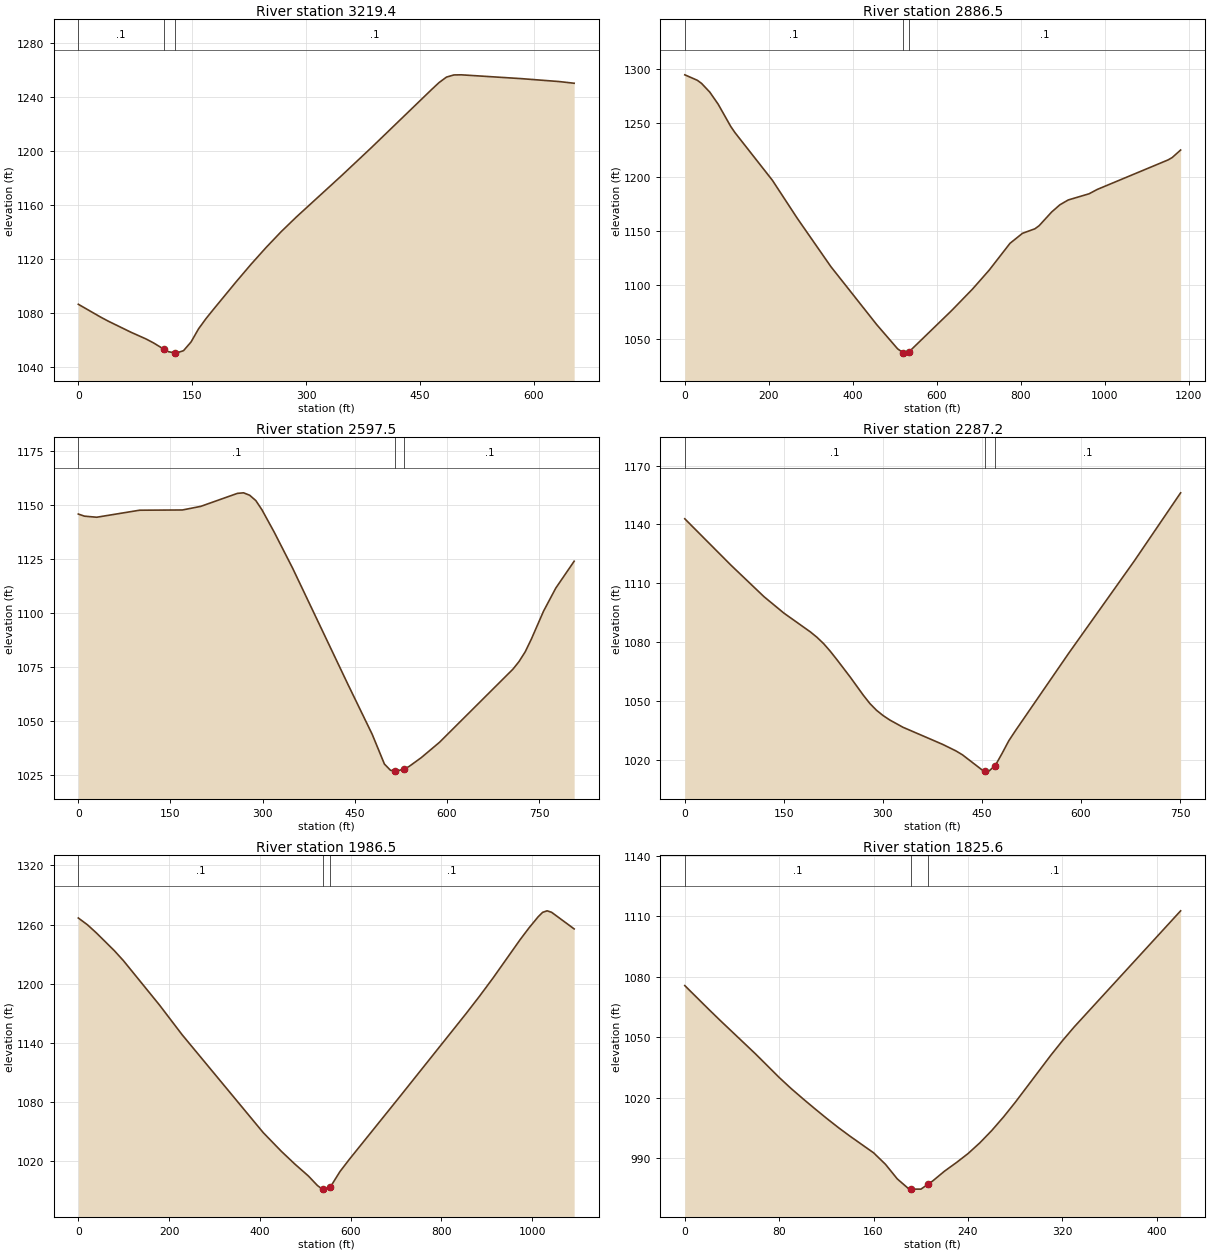
Type RM Length L Ch R = 1 ,3219.4,339.3,332.7,324.6
XS GIS Cut Line= 2
     1945431.517      432951.998     1946053.993      433148.870
#Sta/Elev= 30
       0 1086.46    29.7 1076.87    39.6 1073.92    69.2 1065.80    89.0 1060.84
    98.9 1057.92   112.7 1053.21   118.7 1051.37   127.7 1050.42   128.6 1050.32
   138.5 1052.13   148.4 1058.55   158.3 1068.28   168.2 1075.91   178.0 1082.74
   207.7 1103.02   227.5 1116.10   247.3 1128.50   267.1 1140.17   286.9 1150.93
   346.2 1181.40   385.8 1202.30   464.9 1245.17   474.8 1250.37   484.7 1254.51
   494.6 1256.13   504.5 1256.21   583.6 1253.38   633.1 1251.23   652.9 1249.98
#Mann= 3 , 0 , 0
       0     0.1       0   112.7   0.045       0   127.7     0.1       0
Bank Sta=   112.7,   127.7
Exp/Cntr=0.3,0.1

Type RM Length L Ch R = 1 ,2886.5,305,288.8,273.9
XS GIS Cut Line= 3
     1944861.774      433262.463     1945388.474      433261.665
     1946041.731      433224.798
#Sta/Elev= 30
       0 1295.05    29.8 1290.00    39.8 1287.14    59.6 1278.97    79.5 1267.81
   109.3 1247.25   119.2 1241.60   208.7 1197.20   268.3 1161.76   347.8 1117.23
   457.1 1063.37   506.8 1040.95   519.2 1037.48   526.7 1036.92   534.2 1038.18
   635.8 1076.49   685.3 1096.33   725.0 1113.88   774.5 1138.72   804.3 1148.05
   834.0 1152.26   843.9 1155.08   873.7 1167.77   893.5 1174.52   913.3 1178.98
   962.9 1184.71   982.7 1188.79  1151.3 1216.16  1161.2 1218.41  1181.0 1225.30
#Mann= 3 , 0 , 0
       0     0.1       0   519.2   0.045       0   534.2     0.1       0
Bank Sta=   519.2,   534.2
Exp/Cntr=0.3,0.1

Type RM Length L Ch R = 1 ,2597.5,304.8,310.2,315.7
XS GIS Cut Line= 2
     1945025.053      433887.300     1945634.522      433358.007
#Sta/Elev= 30
       0 1145.94    10.0 1144.97    29.9 1144.47    99.7 1147.72   169.4 1147.83
   199.3 1149.50   259.1 1155.53   269.1 1155.77   279.0 1154.64   289.0 1152.17
   299.0 1147.89   318.9 1137.56   348.8 1120.92   438.5 1067.35   478.4 1043.99
   498.3 1030.22   508.2 1027.33   515.9 1027.03   518.2 1026.94   530.9 1028.00
   538.2 1029.05   558.1 1033.14   588.0 1040.29   707.6 1074.16   717.5 1077.68
   727.5 1082.17   737.5 1088.05   757.4 1101.01   777.3 1111.67   807.2 1124.11
#Mann= 3 , 0 , 0
       0     0.1       0   515.9   0.045       0   530.9     0.1       0
Bank Sta=   515.9,   530.9
Exp/Cntr=0.3,0.1

Type RM Length L Ch R = 1 ,2287.2,297.2,300.7,305.2
XS GIS Cut Line= 2
     1945267.551      433907.682     1945935.906      433565.697
#Sta/Elev= 30
       0 1142.84    70.1 1119.11   120.1 1103.05   150.2 1094.68   190.2 1085.12
   200.2 1082.36   210.2 1079.15   220.2 1075.29   230.2 1071.03   250.3 1062.17
   270.3 1052.84   280.3 1048.57   290.3 1045.14   300.3 1042.44   310.3 1040.20
   330.3 1036.48   390.4 1027.75   410.4 1024.44   420.4 1022.42   450.5 1014.62
   454.8 1014.39   460.5 1014.09   469.8 1016.95   470.5 1017.16   480.5 1023.16
   490.5 1029.52   500.5 1034.63   580.6 1073.88   680.7 1121.35   750.8 1156.09
#Mann= 3 , 0 , 0
       0     0.1       0   454.8   0.045       0   469.8     0.1       0
Bank Sta=   454.8,   469.8
Exp/Cntr=0.3,0.1

Type RM Length L Ch R = 1 ,1986.5,155.6,160.7,164.8
XS GIS Cut Line= 3
     1945244.888      434154.965     1945763.794      433982.936
     1946289.176      433834.753
#Sta/Elev= 30
       0 1266.73    19.9 1259.93    39.8 1251.60    79.5 1233.53    99.4 1223.46
   178.9 1178.44   228.6 1148.43   407.5 1049.05   447.3 1030.16   477.1 1017.19
   506.9 1005.14   526.8  995.48   536.7  992.02   539.2  991.96   546.7  991.78
   554.2  994.10   556.6  994.84   576.4 1009.51   596.3 1021.46   705.5 1083.89
   854.4 1169.78   884.1 1187.44   913.9 1205.92   973.5 1244.75   993.3 1256.80
  1013.2 1267.94  1023.1 1272.46  1033.0 1274.01  1042.9 1272.52  1092.6 1255.66
#Mann= 3 , 0 , 0
       0     0.1       0   539.2   0.045       0   554.2     0.1       0
Bank Sta=   539.2,   554.2
Exp/Cntr=0.3,0.1

Type RM Length L Ch R = 1 ,1825.6,138.3,139.2,139.9
XS GIS Cut Line= 2
     1945600.167      434157.534     1946018.669      434118.495
#Sta/Elev= 30
       0 1075.59    20.0 1064.00    30.0 1058.32    60.0 1041.70    80.1 1030.00
    90.1 1024.58   100.1 1019.53   110.1 1014.63   120.1 1009.84   130.1 1005.25
   140.1 1000.92   160.1  992.67   170.1  987.01   180.1  979.78   190.1  974.72
   191.5  974.72   200.2  974.70   206.5  977.26   210.2  978.77   220.2  983.63
   230.2  987.84   240.2  992.37   250.2  997.70   260.2 1003.75   270.2 1010.48
   280.2 1017.79   310.2 1041.00   320.2 1048.32   330.2 1055.17   420.3 1112.65
#Mann= 3 , 0 , 0
       0     0.1       0   191.5   0.045       0   206.5     0.1       0
Bank Sta=   191.5,   206.5
Exp/Cntr=0.3,0.1

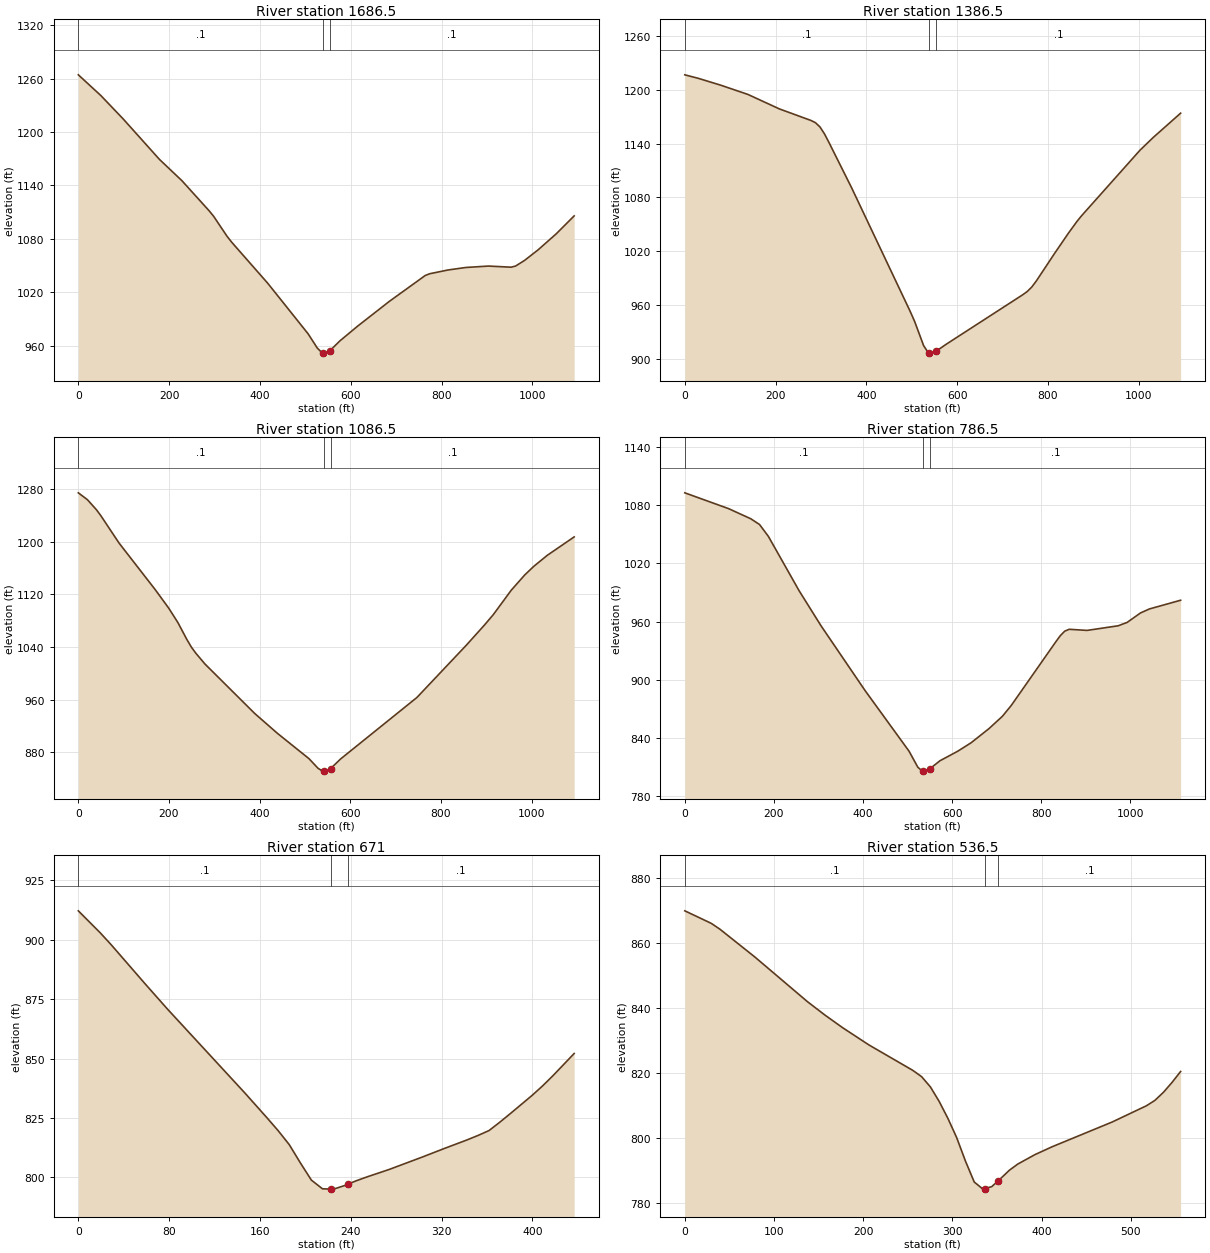
Type RM Length L Ch R = 1 ,1686.5,298.6,299.9,300.5
XS GIS Cut Line= 3
     1945264.183      434308.174     1945809.358      434277.712
     1946354.462      434245.502
#Sta/Elev= 30
       0 1264.28    49.6 1241.01    99.3 1214.42   178.7 1169.26   228.3 1145.26
   287.9 1111.65   297.8 1105.51   327.6 1082.84   337.5 1076.39   417.0 1030.21
   506.3  973.17   526.2  957.38   536.1  952.33   538.5  952.15   546.0  951.58
   553.5  953.94   575.8  965.19   615.5  982.03   685.0 1009.72   764.4 1038.92
   774.4 1040.83   814.1 1044.98   853.8 1047.83   903.4 1049.40   953.1 1048.14
   963.0 1049.40   982.9 1055.76  1012.6 1067.59  1052.4 1085.53  1092.1 1105.77
#Mann= 3 , 0 , 0
       0     0.1       0   538.5   0.045       0   553.5     0.1       0
Bank Sta=   538.5,   553.5
Exp/Cntr=0.3,0.1

Type RM Length L Ch R = 1 ,1386.5,305.5,299.9,294
XS GIS Cut Line= 3
     1945292.443      434575.746     1945838.387      434575.746
     1946384.443      434558.963
#Sta/Elev= 30
       0 1216.96    29.8 1213.04    79.4 1205.36   139.0 1195.08   208.4 1178.90
   277.9 1166.03   287.9 1163.51   297.8 1158.76   307.7 1151.04   317.6 1141.49
   367.3 1091.06   496.3  953.09   506.2  941.79   526.1  914.65   536.0  906.95
   538.4  906.78   546.0  906.24   553.4  908.28   575.7  916.09   744.6  971.45
   754.5  975.07   764.5  980.10   774.4  986.80   814.1 1017.16   843.9 1039.28
   863.8 1053.19   873.7 1059.39  1002.9 1132.86  1032.7 1147.37  1092.3 1174.15
#Mann= 3 , 0 , 0
       0     0.1       0   538.4   0.045       0   553.4     0.1       0
Bank Sta=   538.4,   553.4
Exp/Cntr=0.3,0.1

Type RM Length L Ch R = 1 ,1086.5,297,299.8,302.3
XS GIS Cut Line= 3
     1945367.054      435001.433     1945899.416      434867.740
     1946421.095      434709.490
#Sta/Elev= 30
       0 1274.32    20.0 1263.93    39.9 1248.67    49.9 1239.37    89.8 1198.06
   169.7 1127.18   199.6 1098.95   219.6 1077.29   239.5 1051.49   249.5 1039.82
   259.5 1030.42   279.4 1014.22   389.2  939.04   439.1  909.00   509.0  870.37
   528.9  855.74   538.9  851.46   541.4  851.49   548.9  851.58   556.4  855.10
   578.6  869.90   747.1  963.37   856.2 1042.88   895.8 1073.20   915.6 1089.25
   955.3 1126.44   985.0 1149.57  1004.8 1162.54  1034.6 1179.32  1094.0 1207.34
#Mann= 3 , 0 , 0
       0     0.1       0   541.4   0.045       0   556.4     0.1       0
Bank Sta=   541.4,   556.4
Exp/Cntr=0.3,0.1

Type RM Length L Ch R = 1 ,786.5,116.5,115.5,116.1
XS GIS Cut Line= 3
     1945384.181      435225.346     1945922.774      435159.070
     1946483.261      435055.393
#Sta/Elev= 30
       0 1092.83    98.7 1076.46   148.0 1066.12   167.7 1060.18   187.5 1048.00
   256.5  991.94   305.9  955.66   404.5  889.06   503.2  826.55   522.9  810.08
   532.8  806.00   535.2  806.07   542.7  806.27   550.2  808.54   572.7  816.72
   612.6  826.55   642.6  835.28   682.6  849.83   712.6  862.48   732.6  873.72
   832.6  939.33   842.6  945.60   852.6  950.28   862.6  952.19   902.6  951.03
   972.6  955.81   992.6  959.27  1022.6  969.03  1042.6  973.15  1112.6  982.13
#Mann= 3 , 0 , 0
       0     0.1       0   535.2   0.045       0   550.2     0.1       0
Bank Sta=   535.2,   550.2
Exp/Cntr=0.3,0.1

Type RM Length L Ch R = 1 ,671,137.3,134.5,129.8
XS GIS Cut Line= 3
     1945707.916      435306.855     1946065.517      435252.199
     1946118.610      435199.106
#Sta/Elev= 30
       0  912.08    19.6  902.69    29.3  897.63    58.7  881.47    78.2  870.95
   146.7  835.51   166.2  825.08   176.0  819.69   185.8  813.81   195.5  806.21
   205.3  798.88   215.1  795.22   222.8  795.12   224.9  795.09   234.6  796.59
   237.8  797.22   244.4  798.52   254.2  800.21   273.8  803.35   303.1  808.59
   322.6  812.21   342.2  815.73   352.0  817.63   361.8  819.71   371.1  823.15
   380.5  826.81   399.3  834.31   408.7  838.35   418.1  842.76   436.8  852.10
#Mann= 3 , 0 , 0
       0     0.1       0   222.8   0.045       0   237.8     0.1       0
Bank Sta=   222.8,   237.8
Exp/Cntr=0.3,0.1

Type RM Length L Ch R = 1 ,536.5,534.3,536.3,540
XS GIS Cut Line= 3
     1945603.066      435502.537     1945951.608      435398.645
     1946083.987      435259.564
#Sta/Elev= 30
       0  869.98    29.5  866.14    39.3  864.33    78.6  855.72   137.6  841.93
   157.3  837.78   176.9  833.93   206.4  828.61   255.6  820.76   265.4  818.83
   275.2  815.69   285.1  811.19   294.9  805.95   304.7  800.04   314.6  792.76
   324.4  786.33   334.2  784.14   336.3  784.30   344.0  784.91   351.3  786.70
   363.7  789.95   373.3  791.89   392.5  794.79   411.7  797.21   478.9  804.83
   517.3  809.84   526.9  811.52   536.5  814.02   546.1  817.06   555.7  820.43
#Mann= 3 , 0 , 0
       0     0.1       0   336.3   0.045       0   351.3     0.1       0
Bank Sta=   336.3,   351.3
Exp/Cntr=0.3,0.1